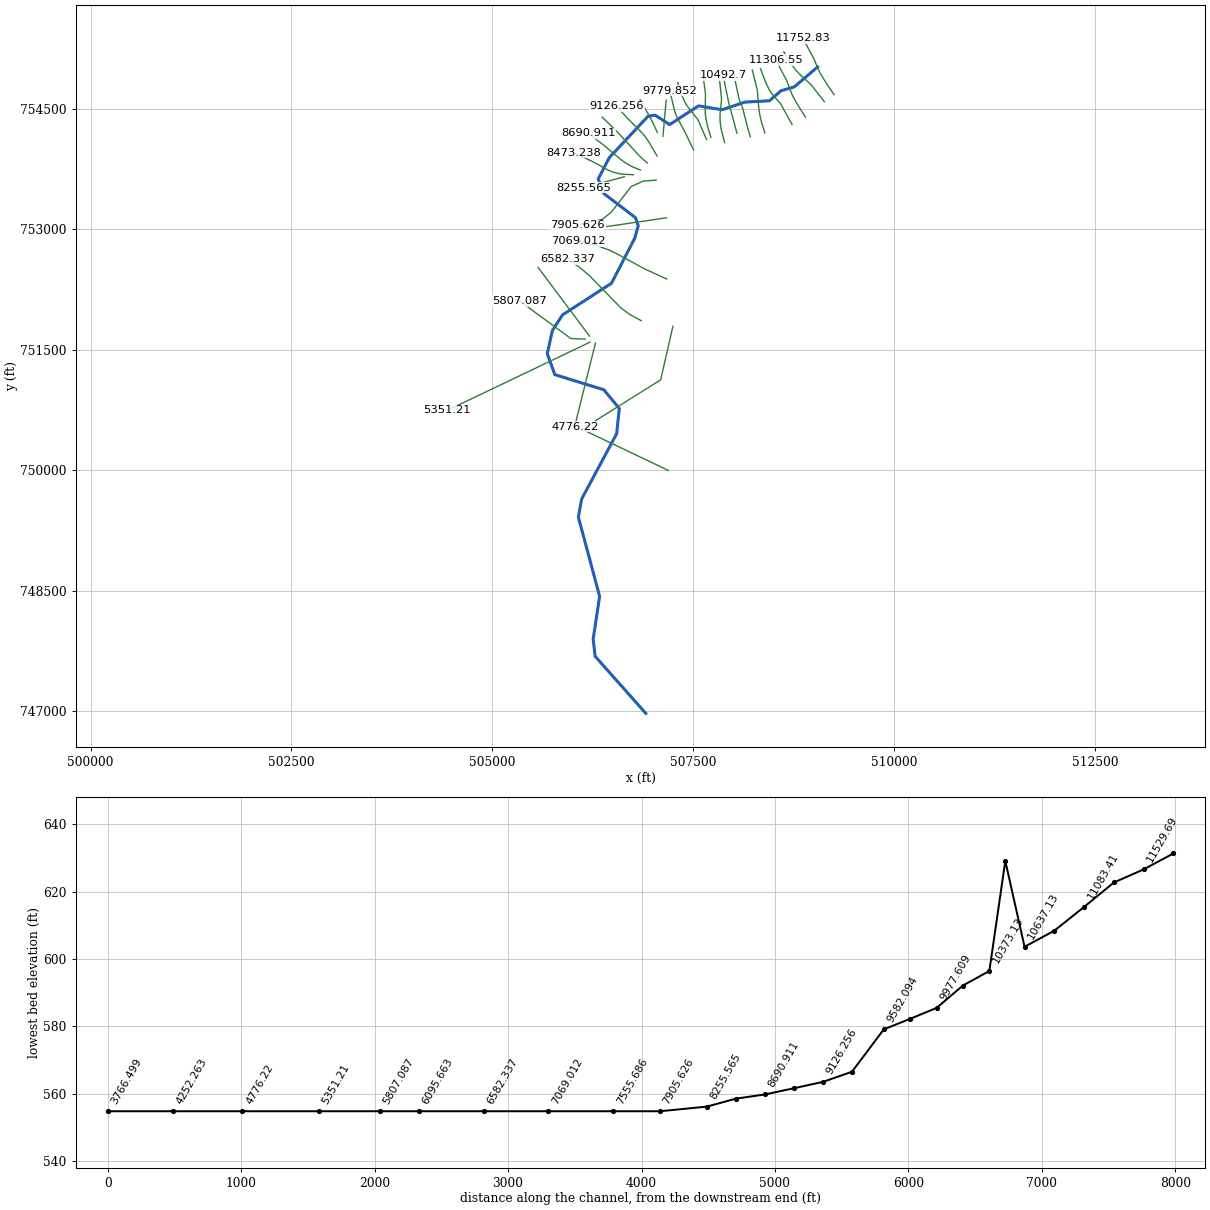
--- 1300_ras.prj (project) ---

Proj Title=1300
Current Plan=p01
Default Exp/Contr=0.3,0.1
English Units
Geom File=g01
Flow File=f01
Plan File=p01
Y Axis Title=Elevation
X Axis Title(PF)=Main Channel Distance
X Axis Title(XS)=Station
BEGIN DESCRIPTION:
RFD model 1300 exported to HEC-RAS
END DESCRIPTION:

--- 1300_ras.p01 (plan) ---

Plan Title=Plan 01
Program Version=4.10
Short Identifier=Plan 01
Geom File=g01
Flow File=f01
Subcritical Flow
Calc Critical at every XS
Secant Critical Depth

--- 1300_ras.f01 (steady flow) ---

Flow Title=Flow 01
Program Version=5.01
Number of Profiles= 6
Profile Names=10yr,25yr,50yr,100yr,100plus,500yr
River Rch & RM=1300,28,11752.83
 1495.43 2447.78 3360.29 4206.04 6140.81 7979.83
River Rch & RM=1300,28,11529.69
 1497.41 2451.42 3365.66 4213.18 6151.24 7993.24
River Rch & RM=1300,28,11306.55
 1503.89 2463.44 3383.44 4236.86 6185.82 8037.87
River Rch & RM=1300,28,11083.41
 1526.31  2504.6 3444.01 4317.26 6303.19 8187.79
River Rch & RM=1300,28,10860.27
 1529.38 2510.28 3452.41 4328.45 6319.53  8208.8
River Rch & RM=1300,28,10637.13
 1556.99 2560.94 3526.93 4427.34 6463.91 8392.59
River Rch & RM=1300,28, 10492.7
 1563.36 2572.76 3544.42 4450.68 6497.99 8436.38
River Rch & RM=1300,28,10373.13
 1565.21 2576.23  3549.6 4457.61 6508.11  8449.5
River Rch & RM=1300,28,10175.37
 1605.77 2651.15 3660.27 4605.01 6723.31 8724.26
River Rch & RM=1300,28,9977.609
 1612.03 2662.79 3677.53 4628.06 6756.96 8767.39
River Rch & RM=1300,28,9779.852
 1613.73 2665.96 3682.23 4634.36 6766.16 8779.24
River Rch & RM=1300,28,9582.094
 1616.81 2671.71 3690.78 4645.81 6782.88 8800.76
River Rch & RM=1300,28,9343.929
 1619.92  2677.5 3699.37 4657.29 6799.65 8822.26
River Rch & RM=1300,28,9126.256
 1625.82 2688.48 3715.68 4679.09 6831.47 8863.06
River Rch & RM=1300,28,8908.583
 1644.77 2723.82 3768.17 4749.33 6934.02  8994.6
River Rch & RM=1300,28,8690.911
 1653.52 2740.24 3792.64 4782.16 6981.96 9056.37
River Rch & RM=1300,28,8473.238
 1656.99 2746.74 3802.33 4795.16 7000.94 9080.82
River Rch & RM=1300,28,8255.565
 1661.19 2754.63  3814.1 4810.97 7024.01 9110.55
River Rch & RM=1300,28,7905.626
 1664.72 2761.31 3824.09 4824.42 7043.65    9136
River Rch & RM=1300,28,7555.686
 1687.79 2804.59 3888.62 4911.05 7170.13 9298.65
River Rch & RM=1300,28,7069.012
 1692.83 2814.07 3902.78 4930.08 7197.91 9334.41
River Rch & RM=1300,28,6582.337
 1695.46 2819.04 3910.22  4940.1 7212.54 9353.32
River Rch & RM=1300,28,6095.663
 1701.87 2831.15 3928.36 4964.55 7248.24 9399.49
River Rch & RM=1300,28,5807.087
 1724.24 2873.35 3991.48 5049.51 7372.28 9559.32
River Rch & RM=1300,28, 5351.21
 1725.82 2876.34 3995.97 5055.56 7381.12 9570.77
River Rch & RM=1300,28, 4776.22
 1726.24 2877.16 3997.19 5057.22 7383.53 9573.89
Boundary for River Rch & Prof#=1300,28,1
Up Type= 0
Dn Type= 2
Boundary for River Rch & Prof#=1300,28,2
Up Type= 0
Dn Type= 2
Boundary for River Rch & Prof#=1300,28,2
Up Type= 0
Dn Type= 2
Boundary for River Rch & Prof#=1300,28,2
Up Type= 0
Dn Type= 2
Boundary for River Rch & Prof#=1300,28,2
Up Type= 0
Dn Type= 2
Boundary for River Rch & Prof#=1300,28,2
Up Type= 0
Dn Type= 2

--- 1300_ras.g01 (geometry) ---

Geom Title=1300
Program Version=4.10

River Reach=1300,28
Reach XY= 30
509046.201757339755018.147534092508755.548566548754769.928796016
 508591.33334598754722.700369589508448.027762084754598.184979884
508141.010972173754581.013592277507856.470316262754485.698152174
507565.092683376754534.594300907507205.278283715754301.476706662
507024.418105125754419.073746945506936.607227055754405.246484954
506455.256924241753890.838106899506316.984186828753626.138417921
506387.224585117753443.087683002506780.737150282753143.180914395
506814.591316937753041.618414395506769.752779841 752883.97485603
 506481.92173782752327.264610117505873.093138456751934.010543344
505745.981625588751737.508080672505682.991129101 751449.74781222
505777.375334589751190.101115128506388.084468452751001.131496719
506579.056690663750768.926635618 506546.50460732750456.426635598
506109.776358424749640.175384784 506069.66679117749417.280880759
506334.273893177748432.152420487506254.119726745 747897.96146613
506278.862923593747685.334546502506908.779021708746975.394014055

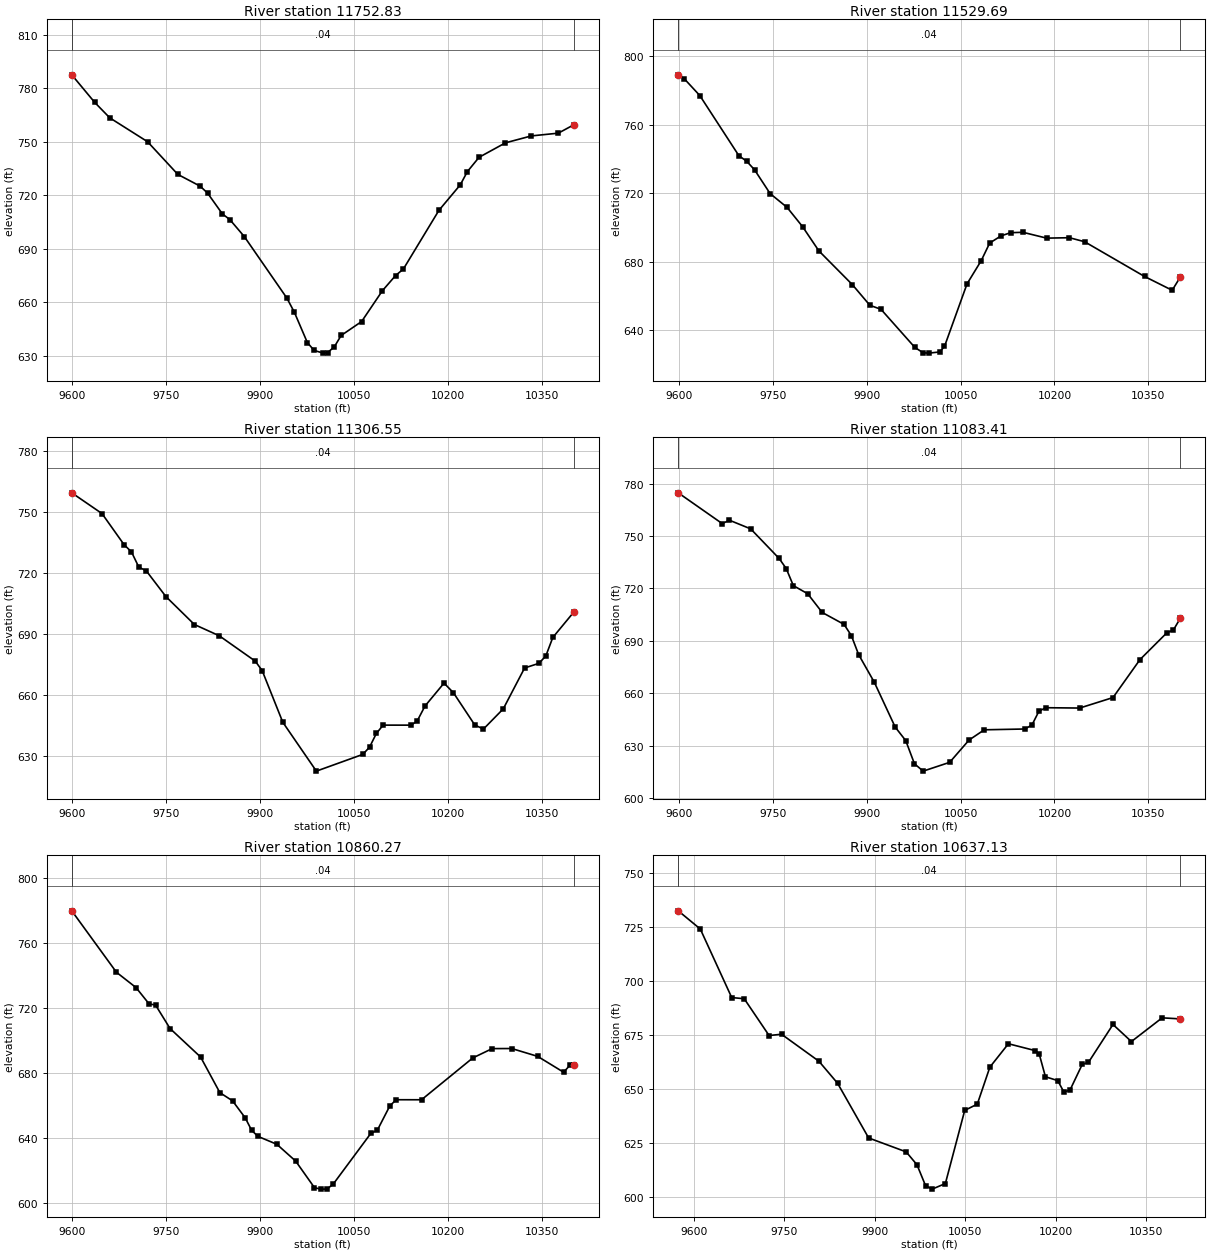
Type RM Length L Ch R = 1 ,11752.83,223.141400,223.141400,223.141400
XS GIS Cut Line= 6
509251.015655401754674.804443579509152.951690079 754819.38037615
509089.916979951754921.678883532509062.444124334754975.603337675
508998.245500692755124.009570761508863.204321513755374.727028881
#Sta/Elev= 30
9599.038787.46719635.524772.05959659.691763.35449720.108749.93819768.441731.6066
9804.108725.01199815.963721.10949839.674709.41679851.389  706.319874.576696.7511
9942.532662.26989954.433654.38519975.383637.23589986.183632.860910000.77631.3511
10007.73631.6448 10018.5634.939410029.26641.246310061.99649.071510095.17666.3565
 10116.2674.863910128.68678.520110185.48711.455210219.55725.739910230.91733.1873
10249.57741.203810291.75749.319510333.13753.2003 10376.1 754.74110400.97759.4461
#Mann= 3 , 0 , 0
9599.038    0.04       09599.038    0.04       010400.97    0.04       0
#XS Ineff= 2 , 0
       0                               0
Bank Sta=9599.038,10400.97
Exp/Cntr=0.3,0.1

Type RM Length L Ch R = 1 ,11529.69,223.141300,223.141300,223.141300
XS GIS Cut Line= 6
509129.844659688754587.378924764508969.756545154754792.207241375
508822.241222593754928.809515167508767.806544978754988.148322496
508704.538763957755075.553239723508626.794673502755206.291871519
#Sta/Elev= 30
9599.068789.03629608.577786.79159633.533 776.9369695.922741.8461  9708.4738.5837
9720.878733.64799745.834719.71919772.934711.65599797.629700.43249823.684686.2881
9877.092666.60589905.177654.51329922.879652.18989976.916629.95819990.119 626.812
    9999626.609810016.64627.285210024.32630.509710060.32667.0341   10083680.6076
10096.54  690.8710114.65695.047410129.91 696.90110149.53697.1328 10187.4693.7242
10223.85693.971910248.01691.6398 10343.8671.356910387.97663.287710400.95671.0421
#Mann= 3 , 0 , 0
9599.068    0.04       09599.068    0.04       010400.95    0.04       0
#XS Ineff= 2 , 0
       0                               0
Bank Sta=9599.068,10400.95
Exp/Cntr=0.3,0.1

Type RM Length L Ch R = 1 ,11306.55,223.141400,223.141400,223.141400
XS GIS Cut Line= 6
508894.331448064754393.996633085 508790.99721359754560.368346798
508742.151042031754646.828325825508717.295224921754701.813663475
 508664.95852712754843.950786103508527.539502289755104.819536383
#Sta/Elev= 30
9599.053 759.4519647.322749.26319682.637733.96289694.409730.42759706.181722.9255
9717.953  721.179749.411708.48269794.904694.7558 9834.68689.21219892.108676.7697
9903.176672.10899936.098646.73769989.735622.725310063.86630.947210074.71634.5187
10085.55 641.25410096.39645.326910140.84645.315710150.58647.259910163.22654.6941
10193.62 665.96710208.62661.248610242.75645.392910256.56643.387810288.25653.3211
10322.34673.414610344.86675.639910356.12 679.22810367.39688.407410400.97700.8966
#Mann= 3 , 0 , 0
9599.053    0.04       09599.053    0.04       010400.97    0.04       0
#XS Ineff= 2 , 0
       0                               0
Bank Sta=9599.053,10400.97
Exp/Cntr=0.3,0.1

Type RM Length L Ch R = 1 ,11083.41,223.141300,223.141300,223.141300
XS GIS Cut Line= 6
508728.953245014 754303.03768091508585.699993655754561.224232408
508480.096368668754681.703053772508445.624880296754732.775656034
508399.870633686 754829.29189645 508336.79266168754995.185075663
#Sta/Elev= 30
9599.086774.68139669.414757.06069680.764759.02049714.814754.06089760.214737.1358
9771.564731.36349782.914721.59969805.824716.95129829.067706.23469863.932699.4127
9875.554 693.0219887.175682.15219912.238666.31629945.563640.68889962.442632.9234
9976.353619.67639990.265615.477810032.61620.512910063.56633.267210087.85639.1199
10152.81 639.57810164.05641.896610175.13649.744110186.04651.754710240.27651.5628
10293.44657.564910336.55679.293810379.35694.580410390.05696.285910400.94702.9505
#Mann= 3 , 0 , 0
9599.086    0.04       09599.086    0.04       010400.94    0.04       0
#XS Ineff= 2 , 0
       0                               0
Bank Sta=9599.086,10400.94
Exp/Cntr=0.3,0.1

Type RM Length L Ch R = 1 ,10860.27,223.141400,223.141400,223.141400
XS GIS Cut Line= 6
508390.430060008754197.309535324508349.893386811754326.518909151
508327.465902536754422.665781993 508313.76190461 754515.74863692
508296.754529085754728.482876292508234.001833828754980.743964674
#Sta/Elev= 30
9599.057780.0465 9670.36742.17849701.693732.7109 9722.51722.67589732.919721.9116
9756.041707.4622 9804.82689.88759835.595667.92259855.877662.86989876.158652.3385
9886.288644.72019896.362640.96219926.584636.07629956.644625.7215  9986.7609.3142
9996.719608.426710006.73608.455510016.74611.571410076.91642.911110086.99644.6764
10107.14659.822410117.21663.554910157.69 663.53910239.54689.329210270.55695.0767
10301.66695.131810343.14690.298310384.62680.514310394.99684.956810400.95 684.748
#Mann= 3 , 0 , 0
9599.057    0.04       09599.057    0.04       010400.95    0.04       0
#XS Ineff= 2 , 0
       0                               0
Bank Sta=9599.057,10400.95
Exp/Cntr=0.3,0.1

Type RM Length L Ch R = 1 ,10637.13,144.424500,144.424500,144.424500
XS GIS Cut Line= 6
508209.744344741 754150.17712152508181.088552058754244.249547094
508114.905889839754503.498705506508078.901231855754591.089191616
508063.681300521754641.365445167507999.535718948754954.481511897
#Sta/Elev= 30
9573.771732.50579610.363724.0856 9662.48692.34889683.217691.8064  9724.5674.7634
9745.141675.35819807.065662.88549838.028652.69539889.631627.33969951.864 620.892
9969.806614.93229984.014605.25479995.018603.642910016.92606.230310049.01640.1025
 10069.9642.998510090.73660.132510121.49670.958910166.15667.761110172.72666.0786
10182.91655.674410203.28653.898710213.47648.621710223.65649.506610244.02661.4286
10254.21 662.30410294.95679.879410325.51671.971210376.53682.959710406.65682.4639
#Mann= 3 , 0 , 0
9573.771    0.04       09573.771    0.04       010406.65    0.04       0
#XS Ineff= 2 , 0
       0                               0
Bank Sta=9573.771,10406.65
Exp/Cntr=0.3,0.1

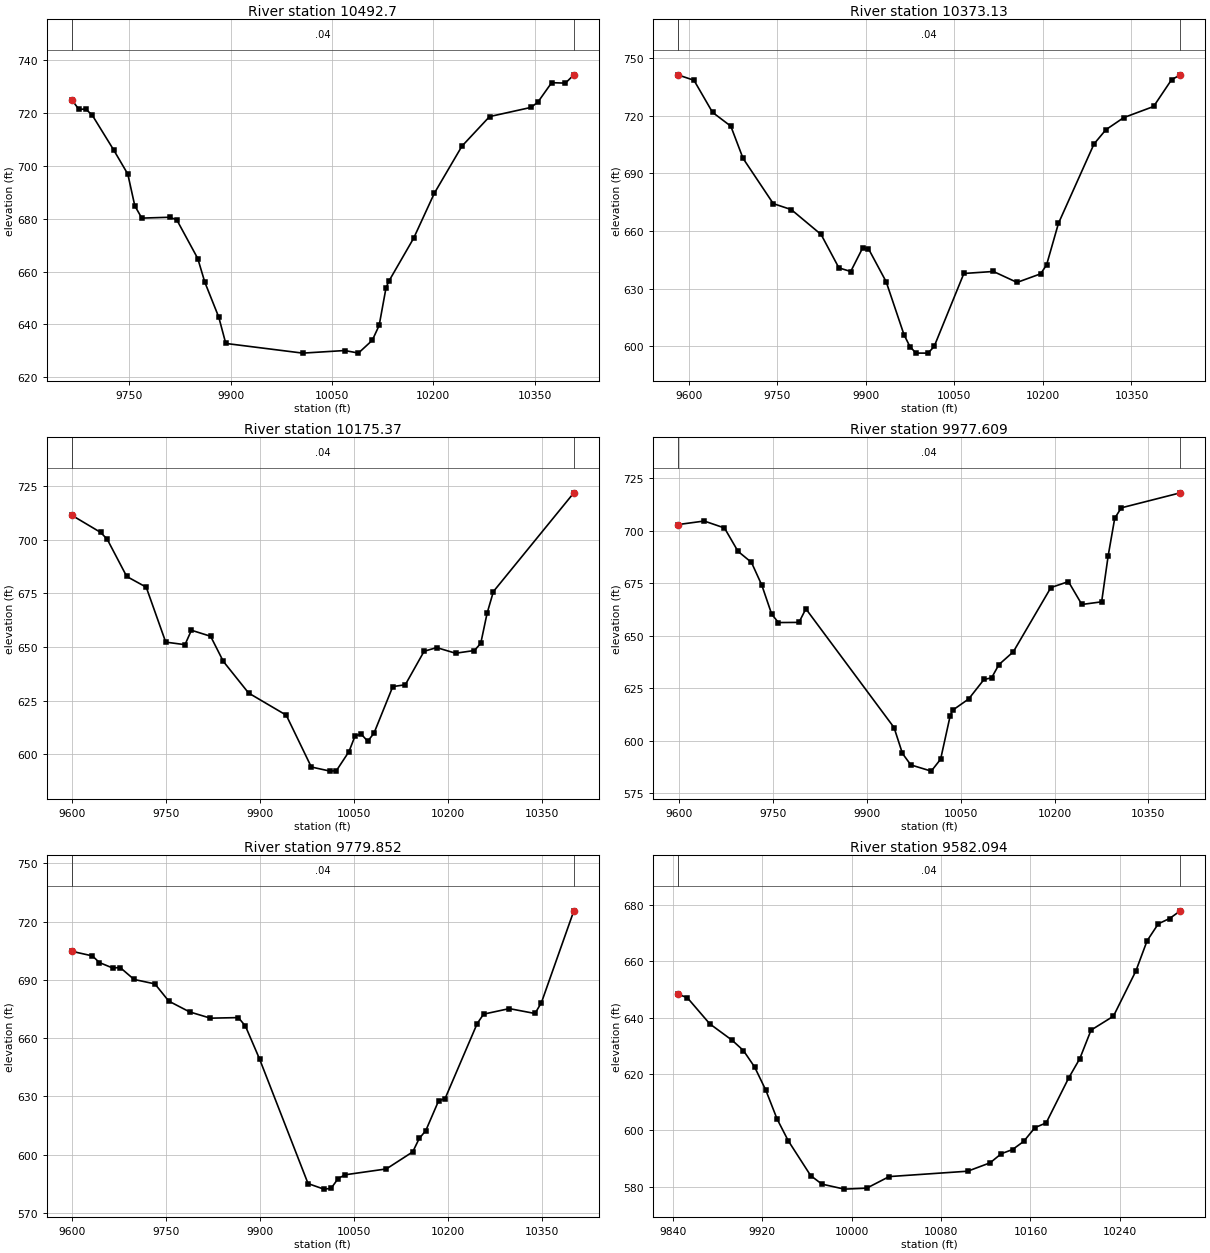
Type RM Length L Ch R = 1 , 10492.7,119.575500,119.575500,119.575500
XS GIS Cut Line= 3
508042.934111804  754194.9119775507939.448987931754579.285294682
507869.754924923754917.195903197
#Sta/Elev= 30
9664.828725.03419675.275721.42089685.631721.50859695.347719.11249727.056705.9479
9747.768696.87629758.124684.8764 9768.48 680.2239809.904680.55069820.261679.5538
9851.329664.90899861.685655.99779882.397642.71849892.753632.771410006.67 629.105
10068.72630.088110089.14629.132110109.57633.959910119.78639.611510129.99653.9197
10134.42656.468110170.83672.618610201.46689.6521 10242.3 707.47610283.14718.6588
10344.41722.131210354.62724.121110375.04 731.49210395.46731.334910407.91734.4726
#Mann= 3 , 0 , 0
9664.828    0.04       09664.828    0.04       010407.91    0.04       0
#XS Ineff= 2 , 0
       0                               0
Bank Sta=9664.828,10407.91
Exp/Cntr=0.3,0.1

Type RM Length L Ch R = 1 ,10373.13,197.757800,197.757800,197.757800
XS GIS Cut Line= 6
507889.765064865754079.571364895507846.584971517 754243.08425574
507832.758124739754349.887995213507832.882202893754430.264919177
507851.489310384754614.463118181507820.533136589754919.749667557
#Sta/Elev= 30
9582.387741.24239609.042738.49969640.439721.80869671.458714.59149692.137 697.854
9743.354674.27729773.807671.18059824.332658.21979854.461640.84859874.488638.9442
9894.496651.09039904.501650.83099934.523633.63099964.701606.10059974.771599.8545
9985.006596.483410005.57596.461610015.86599.956310066.12637.923310116.14638.9673
10156.17633.270210196.21637.747810206.25642.435510226.31664.018310286.57705.3584
 10306.7712.7641 10336.9719.061510387.44724.844110417.77738.740810432.69741.3275
#Mann= 3 , 0 , 0
9582.387    0.04       09582.387    0.04       010432.69    0.04       0
#XS Ineff= 2 , 0
       0                               0
Bank Sta=9582.387,10432.69
Exp/Cntr=0.3,0.1

Type RM Length L Ch R = 1 ,10175.37,197.757900,197.757900,197.757900
XS GIS Cut Line= 6
507718.855105438754141.174694416507675.668200305754287.021324494
507652.500193352754405.368541298507648.322671303754467.114777244
507651.715928981754688.821424257 507617.22488471754931.592098769
#Sta/Elev= 30
9599.074711.50029645.066703.51029655.561 700.358 9686.86682.93979717.986677.9517
9749.111652.32299779.897651.13229790.151657.86639820.817655.05479841.084643.3525
9881.511 628.5789941.635 618.2539981.661594.078310011.69592.1577 10021.7592.3671
10041.71601.226510051.72608.709710061.73609.309110071.74606.095210081.75609.8603
10111.75631.574810131.76 632.43710161.79 648.05110181.86649.7724   10212647.1445
10242.22648.4126 10252.3651.785510262.37665.746410272.49675.921910400.95 721.951
#Mann= 3 , 0 , 0
9599.074    0.04       09599.074    0.04       010400.95    0.04       0
#XS Ineff= 2 , 0
       0                               0
Bank Sta=9599.074,10400.95
Exp/Cntr=0.3,0.1

Type RM Length L Ch R = 1 ,9977.609,197.757800,197.757800,197.757800
XS GIS Cut Line= 6
507664.735355739754116.468315018507555.822404216754366.288172272
 507434.56505122754517.214156405507390.752084604754587.719782271
507350.922084621754682.587306283507306.618440247754824.981857461
#Sta/Elev= 30
9599.049702.90639640.568704.58369672.894701.27739694.445690.17969715.995684.8839
9732.581674.00699748.321660.21679759.097656.2466 9791.85656.32119802.885662.7792
9943.731 606.2529957.099593.94739970.467588.479910003.13585.510410018.09591.1797
10033.32611.776410037.17614.484310062.92619.867810087.36629.136410099.51629.9364
10111.23636.229110134.23642.325810194.21672.900410222.24675.739810243.67664.8564
10275.28666.114110285.75688.111610296.22705.949410306.69710.866810400.93718.0106
#Mann= 3 , 0 , 0
9599.049    0.04       09599.049    0.04       010400.93    0.04       0
#XS Ineff= 2 , 0
       0                               0
Bank Sta=9599.049,10400.93
Exp/Cntr=0.3,0.1

Type RM Length L Ch R = 1 ,9779.852,197.757800,197.757800,197.757800
XS GIS Cut Line= 6
507503.164203682 753985.25753656507395.994611697 754209.03774524
507308.137589241754371.035607138507284.302532592754422.150975501
507259.662632574754499.465626739507207.728899772754725.486819479
#Sta/Elev= 30
9599.015704.75639631.992702.3697 9643.08698.96659664.221696.16099676.343696.3877
9698.518690.25129731.781687.96349753.956679.09649787.219  673.549820.481670.3137
9865.121670.6071 9876.39666.22829898.928649.30749976.405 585.14110001.66582.2765
 10013.1582.637810024.54587.743410035.82589.669810101.49592.677210143.61601.4641
10154.01608.3711 10164.4 612.36910184.98627.783810195.24628.863410246.54667.5195
 10256.8672.379910297.84675.236610338.88672.723210349.15678.317810400.95725.5903
#Mann= 3 , 0 , 0
9599.015    0.04       09599.015    0.04       010400.95    0.04       0
#XS Ineff= 2 , 0
       0                               0
Bank Sta=9599.015,10400.95
Exp/Cntr=0.3,0.1

Type RM Length L Ch R = 1 ,9582.094,238.164800,238.164800,238.164800
XS GIS Cut Line= 2
507122.127703577754156.897034049507162.254588336754604.628590316
#Sta/Elev= 30
9844.627648.25929852.762647.02259872.843637.76099892.923631.92729902.963628.3044
9913.003622.46579923.043614.23199933.083604.05279943.123596.29829963.203583.9369
9973.243580.92769993.323579.1456 10013.4579.491910033.48583.592810103.76585.5012
10123.84588.473810133.88591.708910143.92593.178710153.96596.0822   10164600.9623
10174.04602.623310194.13618.507310204.17625.430610214.21635.531510234.29640.4841
10254.37  656.5110264.41667.214510274.45673.240510284.49675.096610294.15677.8397
#Mann= 3 , 0 , 0
9844.627    0.04       09844.627    0.04       010294.15    0.04       0
#XS Ineff= 2 , 0
       0                               0
Bank Sta=9844.627,10294.15
Exp/Cntr=0.3,0.1

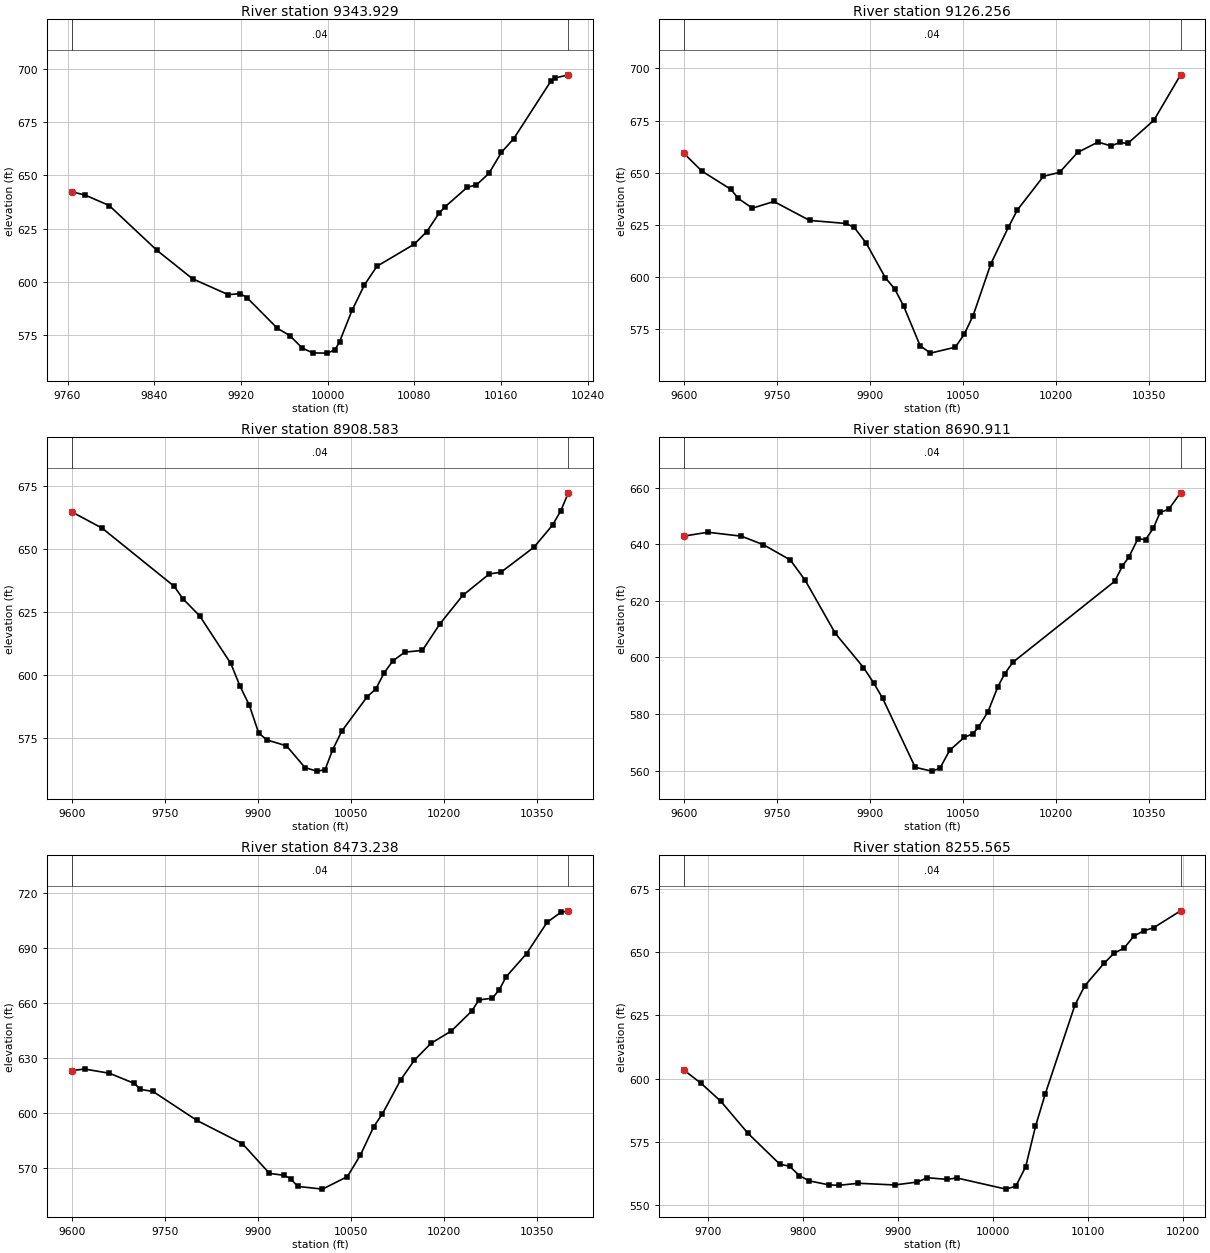
Type RM Length L Ch R = 1 ,9343.929,217.672800,217.672800,217.672800
XS GIS Cut Line= 3
507052.433640629754203.359742731506986.963460177754346.971751347
 506839.12756899754608.852472931
#Sta/Elev= 30
9763.696642.28419776.489640.62929798.469635.77829842.429614.8145  9875.4601.4297
 9908.37593.9884 9919.36594.45839925.521 592.6539953.713578.21029965.196574.8142
 9976.68568.92699986.547566.66529999.647566.578110006.89568.126310011.13571.9586
10022.61586.6499 10034.1598.588610045.58607.279510080.03 617.66210091.51623.4728
   10103632.2318 10108.6635.218210128.94644.338110137.45645.441410148.93650.8256
10160.41660.6584 10171.9667.152710206.35694.276610210.31695.580810222.25697.0487
#Mann= 3 , 0 , 0
9763.696    0.04       09763.696    0.04       010222.25    0.04       0
#XS Ineff= 2 , 0
       0                               0
Bank Sta=9763.696,10222.25
Exp/Cntr=0.3,0.1

Type RM Length L Ch R = 1 ,9126.256,217.672800,217.672800,217.672800
XS GIS Cut Line= 6
 507049.67778824753910.127611069506941.164403469754094.261813699
506894.884045601754160.798179157506819.570039401754242.580011804
506676.984677856 754383.60852996506546.743102904754529.132262055
#Sta/Elev= 30
9599.039659.33719628.375650.75919675.405641.98559686.926637.67479709.968633.0113
 9744.53636.21159802.135627.14539860.424625.6863 9874.13623.83619893.703616.1899
9924.331599.73519939.638594.28689954.054586.04449980.696567.06189997.298563.5598
10037.34566.399810051.72572.5564 10066.1581.516410094.85606.402810122.83623.7618
10137.72632.221510179.67648.286210205.68650.158610234.71659.687910267.79664.6769
10288.98662.803210302.47664.482210315.76 664.02110358.08675.180310400.99696.8935
#Mann= 3 , 0 , 0
9599.039    0.04       09599.039    0.04       010400.99    0.04       0
#XS Ineff= 2 , 0
       0                               0
Bank Sta=9599.039,10400.99
Exp/Cntr=0.3,0.1

Type RM Length L Ch R = 1 ,8908.583,217.672800,217.672800,217.672800
XS GIS Cut Line= 6
506929.356329954753823.028484351506875.794575512753868.240135832
506816.657385894753925.087888523506574.001279411754189.446930796
506485.212784587754278.972608606506366.620953256 754393.53034733
#Sta/Elev= 30
9599.027664.89939648.593658.34279764.801635.21599778.573630.34579806.119 623.385
 9856.13604.51559871.109595.45319886.089587.86869901.068576.89319914.153574.1043
9946.007571.74389975.966563.0772 9994.74561.676210008.17562.169810020.69570.2635
10035.48577.658410076.55591.352410090.24594.378510103.93600.891210117.84 605.566
   10137609.0183 10165.4609.7291 10193.8620.314410230.51631.591610273.57640.1698
10292.02640.785410345.53650.787310375.44659.563610388.71665.247710400.99672.4245
#Mann= 3 , 0 , 0
9599.027    0.04       09599.027    0.04       010400.99    0.04       0
#XS Ineff= 2 , 0
       0                               0
Bank Sta=9599.027,10400.99
Exp/Cntr=0.3,0.1

Type RM Length L Ch R = 1 ,8690.911,217.672800,217.672800,217.672800
XS GIS Cut Line= 6
506841.469205422753735.704099106506723.912109061753784.352133128
506636.047508083753838.616315774506570.873738946753889.036529155
506388.052198299754044.284963731506189.652185591754194.712562159
#Sta/Elev= 30
9599.065642.89119637.965644.25329692.074642.87089727.713639.84589771.101634.4606
9794.986627.30489843.699608.52359889.193596.44169905.535591.05029919.888585.6532
9972.701561.17489999.108559.828110012.36560.768810028.34567.187810052.08571.8018
10065.31572.957410074.41575.266210090.15580.816710105.89 589.555 10117.1594.2246
10130.05598.248110294.73626.928610307.18632.353410317.54635.478810332.08641.9344
10344.53641.661810356.98 645.674 10367.9651.237410381.88652.392210400.99658.1878
#Mann= 3 , 0 , 0
9599.065    0.04       09599.065    0.04       010400.99    0.04       0
#XS Ineff= 2 , 0
       0                               0
Bank Sta=9599.065,10400.99
Exp/Cntr=0.3,0.1

Type RM Length L Ch R = 1 ,8473.238,217.672800,217.672800,217.672800
XS GIS Cut Line= 6
506756.226561141753677.322071395506604.374713418753685.431975658
506499.529608646753710.215300598506437.207502779 753737.58699353
506233.709015455753847.842453055506013.867121546753949.691181871
#Sta/Elev= 30
9599.082623.1359 9620.32623.96399660.341621.66539700.367616.15059710.411612.8658
9730.497 611.7859801.436 595.9929874.772583.37539918.573 567.1689942.462566.0653
9952.625564.34499964.068 560.06910004.15558.580210044.29565.3842 10065.3577.0814
10086.91592.603210101.01599.617910130.63618.232110152.48628.787310179.31 637.976
10212.38 644.74210245.44655.658410256.46 661.568 10278.5662.576110289.52667.1684
10300.54674.156310333.61686.871410366.67703.861510388.71709.246310400.98710.1123
#Mann= 3 , 0 , 0
9599.082    0.04       09599.082    0.04       010400.98    0.04       0
#XS Ineff= 2 , 0
       0                               0
Bank Sta=9599.082,10400.98
Exp/Cntr=0.3,0.1

Type RM Length L Ch R = 1 ,8255.565,349.939400,349.939400,349.939400
XS GIS Cut Line= 2
506642.683371335753652.483833998506137.475038022753517.067167327
#Sta/Elev= 30
9674.204603.41389692.511 598.1019713.217591.01249741.735578.36069775.335566.1058
9785.688565.28449796.041561.53229806.394559.4941  9827.1557.89689837.453557.7283
9858.159558.53459896.233557.87669920.277559.0322 9930.63560.73339951.336560.0902
9961.689560.642910013.45556.222710023.81557.394910034.16565.055510044.51581.0627
10054.87594.021110085.93628.994210096.28 636.69810116.98645.758410127.34649.7013
10137.69651.623710148.04656.4056 10158.4658.498610168.75659.693910197.25666.4257
#Mann= 3 , 0 , 0
9674.204    0.04       09674.204    0.04       010197.25    0.04       0
#XS Ineff= 2 , 0
       0                               0
Bank Sta=9674.204,10197.25
Exp/Cntr=0.3,0.1

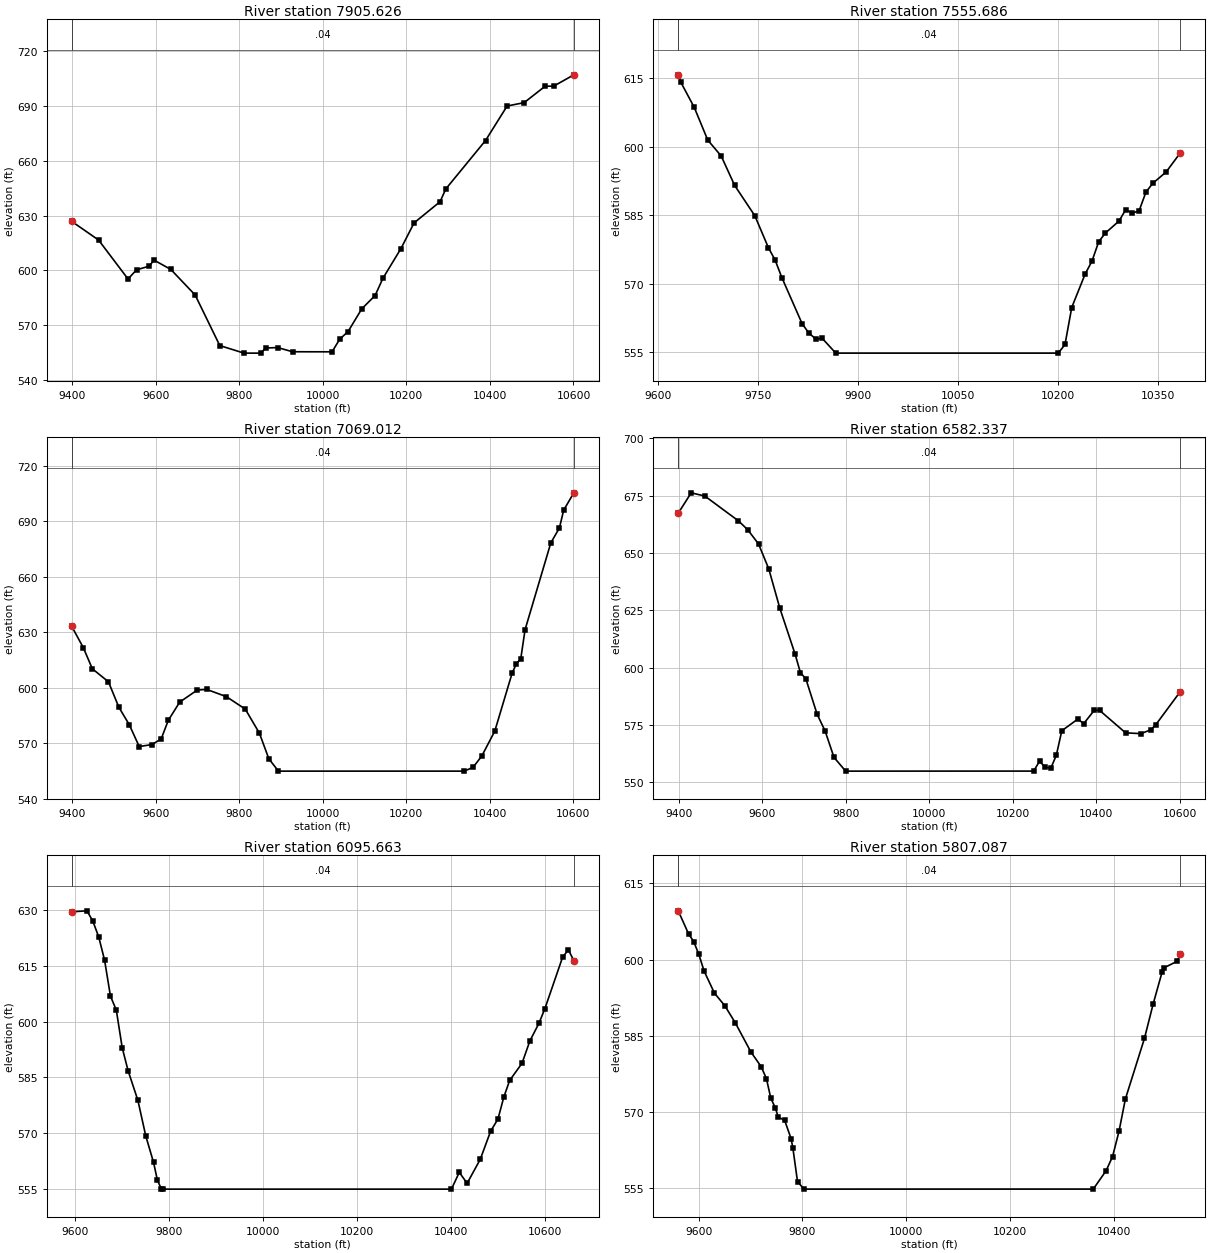
Type RM Length L Ch R = 1 ,7905.626,349.939500,349.939500,349.939500
XS GIS Cut Line= 6
 507039.11604974753610.885812021506879.212761365753599.127850801
 506728.24761703753531.570315963 506483.11290474753216.276299215
506371.324780846753124.268678793506056.650630305753046.390275604
#Sta/Elev= 30
9399.042626.81319463.207616.63729533.721595.35289554.063600.36329585.083602.4066
9595.463605.72769636.155600.57779694.405586.59839753.369558.98119811.359554.8545
9851.059 554.8579863.707557.67119892.136557.88249927.555555.607410022.08555.5661
10040.61562.525410060.33 566.60410093.37579.0879 10125.2586.332710143.78595.7133
10186.75611.8657 10218.5626.012310280.66637.5842 10294.4644.554810389.42670.9827
10441.19689.867610481.94691.699710532.37700.709310552.43700.6821 10600.9706.8964
#Mann= 3 , 0 , 0
9399.042    0.04       09399.042    0.04       0 10600.9    0.04       0
#XS Ineff= 2 , 0
       0                               0
Bank Sta=9399.042,10600.9
Exp/Cntr=0.3,0.1

Type RM Length L Ch R = 1 ,7555.686,486.674500,486.674500,486.674500
XS GIS Cut Line= 2
507168.725037992753142.067167327506423.933371335753032.692167327
#Sta/Elev= 30
9630.804615.73919634.569614.14729654.784608.62729674.998601.48489695.213597.9774
9715.427591.53589745.749 584.8869765.963577.92779776.071575.20869786.178571.3724
  9816.5561.31379826.607559.24249836.714557.99099846.821558.06629867.036554.8545
10200.58554.854510210.68556.742210220.79564.8358   10241572.200410251.11574.9596
10261.22579.230710271.33581.140910291.54583.729310301.65586.216210311.76 585.483
10321.86586.020910331.97590.052610342.08591.980210362.29594.479810383.58598.6638
#Mann= 3 , 0 , 0
9630.804    0.04       09630.804    0.04       010383.58    0.04       0
#XS Ineff= 2 , 0
       0                               0
Bank Sta=9630.804,10383.58
Exp/Cntr=0.3,0.1

Type RM Length L Ch R = 1 ,7069.012,486.674400,486.674400,486.674400
XS GIS Cut Line= 6
507170.124183366752379.635084455506884.872241832752510.868001888
506547.992388513752694.042874562506449.609442794752741.555567511
506301.179446191 752795.57971851506071.326863831752853.626112412
#Sta/Elev= 30
9399.023633.04839426.472621.67139448.322610.15699486.834603.13599511.664589.4266
9536.494580.03659560.494568.14499590.961569.20229613.134572.27629629.979582.2654
 9657.48592.17659699.464598.68119722.005599.02889769.278595.09649814.371588.3783
9848.192575.36859870.911561.46599893.848554.854510338.73554.854510359.83556.9441
10380.61563.030410411.69576.478810453.11607.753110463.47612.992810473.83615.5201
10484.19631.306910545.82678.224910566.36686.285810576.64695.938810600.96705.2804
#Mann= 3 , 0 , 0
9399.023    0.04       09399.023    0.04       010600.96    0.04       0
#XS Ineff= 2 , 0
       0                               0
Bank Sta=9399.023,10600.96
Exp/Cntr=0.3,0.1

Type RM Length L Ch R = 1 ,6582.337,486.674500,486.674500,486.674500
XS GIS Cut Line= 6
506852.351484208751861.545032178  506706.0418058751940.560698575
 506596.20646878752023.005323679506198.196315976752431.182029904
506077.835542522752530.997054077505935.156192941752625.508098857
#Sta/Elev= 30
9399.061667.28029430.054676.17529462.724674.7749 9543.18663.95179565.513660.0631
9591.276653.89129615.762643.0256 9642.39625.80799678.771605.87079691.619597.7489
9704.544 595.0989731.504579.6661 9750.63572.35089771.943560.84139799.888554.8545
10249.89554.872410263.93559.146410277.57556.591910290.81556.087810304.05561.7085
10317.29572.460410355.45577.525810369.83575.592210395.24581.431410407.94581.3085
10469.94571.548810506.67571.194410530.39572.887410542.18575.066710600.96589.5325
#Mann= 3 , 0 , 0
9399.061    0.04       09399.061    0.04       010600.96    0.04       0
#XS Ineff= 2 , 0
       0                               0
Bank Sta=9399.061,10600.96
Exp/Cntr=0.3,0.1

Type RM Length L Ch R = 1 ,6095.663,288.575700,288.575700,288.575700
XS GIS Cut Line= 2
506209.356715381751669.110436559505568.865262359752524.312092543
#Sta/Elev= 30
9592.445629.5859 9624.79629.84429637.284627.06399649.778622.81669662.271616.5503
9674.765606.85879687.259603.08469699.752592.97659712.246586.78679733.167 578.768
9749.849569.21319766.531562.03549774.714557.22579783.213554.89429787.207554.8545
10400.44554.854510417.12559.3849 10433.8556.418910461.86562.918710483.85570.4847
10499.34573.709610511.84579.643910524.33584.151210550.58588.757510567.26594.7618
 10586.8 599.59110599.29 603.49210636.77617.279910649.27619.3687 10660.9616.4053
#Mann= 3 , 0 , 0
9592.445    0.04       09592.445    0.04       0 10660.9    0.04       0
#XS Ineff= 2 , 0
       0                               0
Bank Sta=9592.445,10660.9
Exp/Cntr=0.3,0.1

Type RM Length L Ch R = 1 ,5807.087,455.877400,455.877400,455.877400
XS GIS Cut Line= 3
506154.769375592751632.718876734 505976.45073247751639.997188687
505339.598435432 752105.80915451
#Sta/Elev= 30
9560.806609.61289580.592605.1044  9590.6603.56169600.608601.02749610.616597.7622
9630.633593.4146 9650.65 590.9299670.666587.59279700.691 581.8659720.708578.9366
9730.716576.60019739.273572.70599747.747570.8916 9753.46569.03859765.849568.3929
9778.239564.79249781.624563.01059790.628556.35539803.017554.854510360.54554.8591
10385.32558.484210397.71561.2528 10410.1 566.20110422.49572.604810459.17584.4969
10476.11591.340910493.05597.513910496.83598.403610521.61 599.648 10528.3601.0436
#Mann= 3 , 0 , 0
9560.806    0.04       09560.806    0.04       0 10528.3    0.04       0
#XS Ineff= 2 , 0
       0                               0
Bank Sta=9560.806,10528.3
Exp/Cntr=0.3,0.1

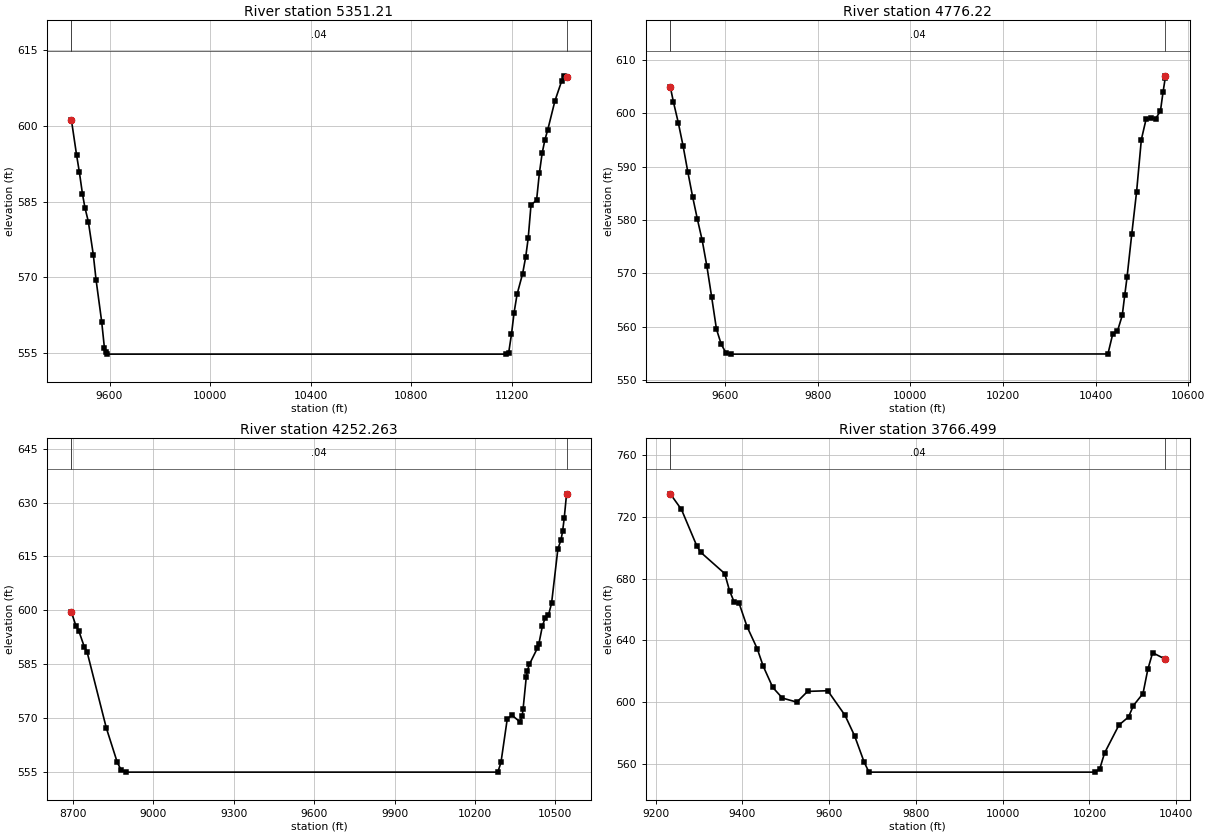
Type RM Length L Ch R = 1 , 5351.21,574.989200,574.989200,574.989200
XS GIS Cut Line= 2
 506213.47868517751593.978322148504437.437018514 750745.01998882
#Sta/Elev= 30
9448.408601.0821 9468.89594.19079479.973590.80759492.414586.45419502.141583.7879
9515.602581.03879535.392574.49719546.476569.48939568.643561.29889579.727556.0109
9585.164555.2442 9590.81554.854511175.78554.854511186.87555.163911197.95558.7918
11208.28563.052911220.12566.662211242.29 570.77311254.66 574.11311264.45577.7815
11275.54584.3302 11297.7585.264511308.79590.596811319.87594.552211330.96597.2194
11342.04599.1595 11370.6604.864611397.46608.812511408.54609.829211416.92609.5115
#Mann= 3 , 0 , 0
9448.408    0.04       09448.408    0.04       011416.92    0.04       0
#XS Ineff= 2 , 0
       0                               0
Bank Sta=9448.408,11416.92
Exp/Cntr=0.3,0.1

Type RM Length L Ch R = 1 , 4776.22,523.957000,523.957000,523.957000
XS GIS Cut Line= 2
   506282.139835751581.770692974506023.759760231750544.611237854
#Sta/Elev= 30
9481.873604.9445 9488.85602.04469499.156598.23429509.461593.90759519.767588.9974
9530.073584.36759540.378580.14859550.684576.2384 9560.99571.28589571.295 565.524
9581.601559.54019591.907556.70429602.212555.06649612.518554.854510426.66554.8831
10436.97558.606310447.27559.180210457.58 562.10810462.87565.865310467.89569.2442
10478.19577.4213 10488.5585.2523 10498.8595.051310509.11598.903510519.41599.0382
10529.72598.976110540.03600.4129 10545.6603.934110550.33606.554510550.73606.9963
#Mann= 3 , 0 , 0
9481.873    0.04       09481.873    0.04       010550.73    0.04       0
#XS Ineff= 2 , 0
       0                               0
Bank Sta=9481.873,10550.73
Exp/Cntr=0.3,0.1

Type RM Length L Ch R = 1 ,4252.263,485.764700,485.764700,485.764700
XS GIS Cut Line= 3
507246.464796305 751791.89498882507093.687018514751125.228322148
506107.575907409750507.172766611
#Sta/Elev= 30
8693.918599.42958711.251595.5231 8721.51594.22738742.028589.76838752.288588.3962
8824.102567.17738865.139557.54738879.546555.44618895.917554.854510285.06554.8571
10296.86557.554410320.46569.738210338.62570.704510367.67568.841410376.28570.6337
10379.47572.508910391.27581.347210395.11583.088910403.07584.932110432.77589.4143
10438.48590.6967 10451.6595.626110462.08597.918610473.89598.545210485.69 601.936
10509.29617.085410521.09619.656410526.92622.052810532.89625.613610541.66632.4459
#Mann= 3 , 0 , 0
8693.918    0.04       08693.918    0.04       010541.66    0.04       0
#XS Ineff= 2 , 0
       0                               0
Bank Sta=8693.918,10541.66
Exp/Cntr=0.3,0.1

Type RM Length L Ch R = 1 ,3766.499,0.000000,0.000000,0.000000
XS GIS Cut Line= 2
507188.289674789749998.737840414506158.408531576 750490.02389811
#Sta/Elev= 30
9233.917734.74929259.721724.63539294.913701.19829304.039696.98189359.436683.1914
9370.516672.14539381.595664.53649392.675663.91479411.043648.77889434.269634.6815
9448.073623.36939470.232609.56279492.391 602.7229525.629600.10039550.399 607.043
9596.851607.47319636.424591.67229658.584578.42469680.743561.33029691.822554.8545
10212.56554.854510223.64556.905410234.72 567.17910267.96585.305610290.12590.5351
 10301.2597.885210323.36  605.6710334.43621.205510345.51632.023110374.98 627.863
#Mann= 3 , 0 , 0
9233.917    0.04       09233.917    0.04       010374.98    0.04       0
#XS Ineff= 2 , 0
       0                               0
Bank Sta=9233.917,10374.98
Exp/Cntr=0.3,0.1